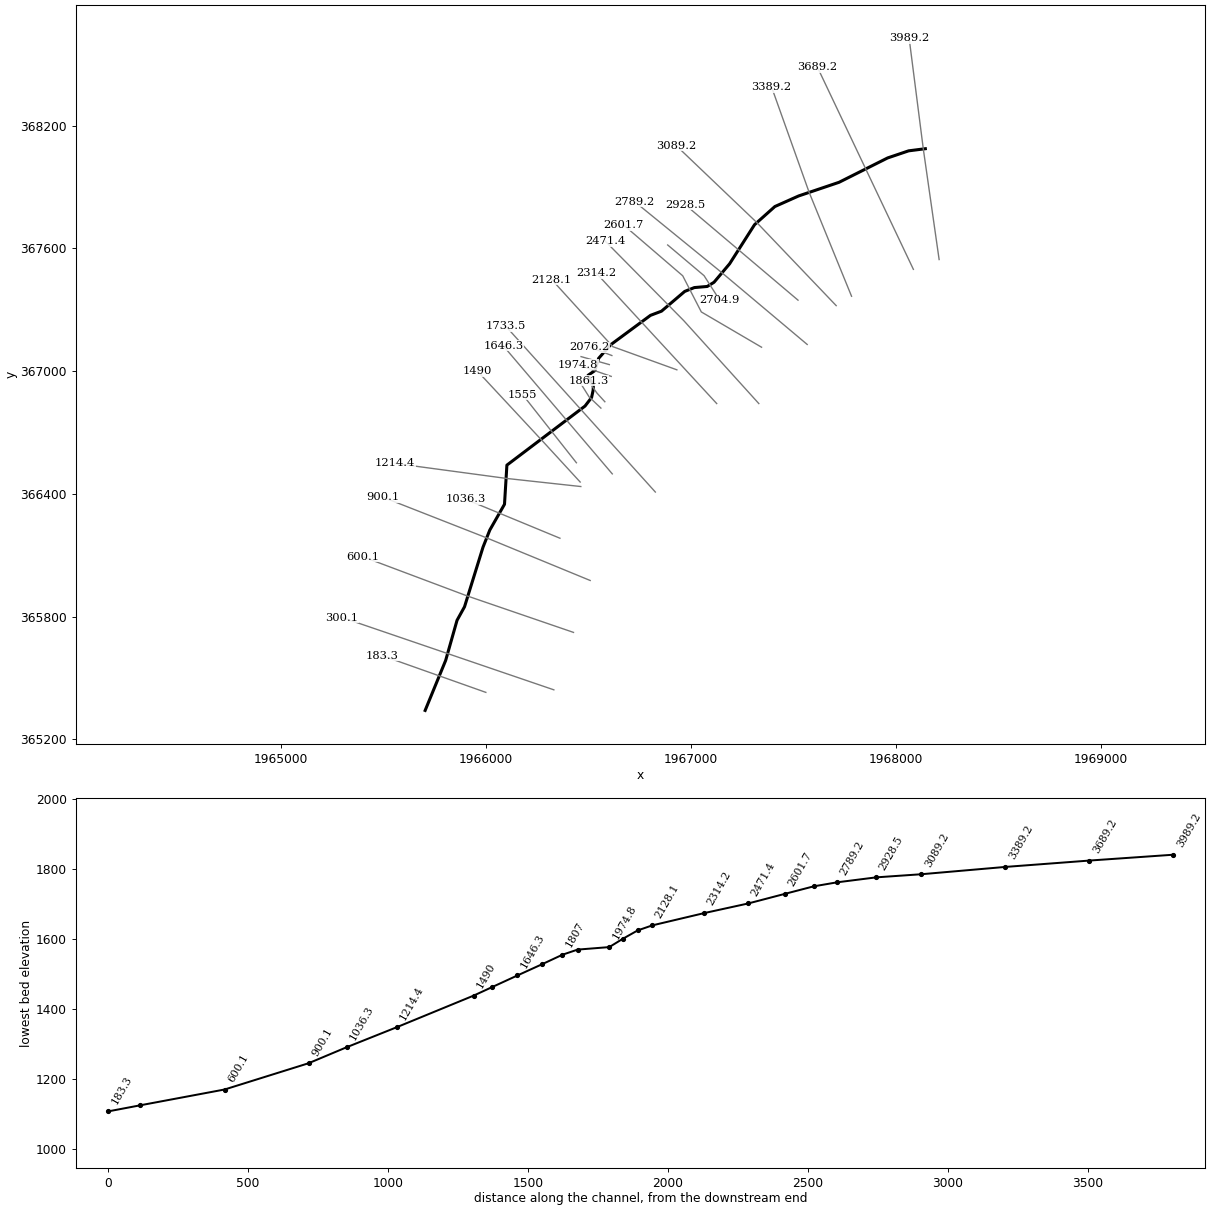
--- NP24.prj (project) ---

Proj Title=NP24
Current Plan=p01
Geom File=g01
Flow File=f01
Plan File=p01
DSS Export Rating Curves=0
DSS Export Rating Curve Sorted=0
DSS Export Volume Flow Curves=0
DXF OffsetX=0
DXF OffsetY=0
DXF ScaleX=0
DXF ScaleY=0

--- NP24.p01 (plan) ---

Plan Title=Floodplain
Program Version=4.00
Geom File=g01
Flow File=f01
K Sum by GR=0
Std Step Tol=0.01
Critical Tol=0.01
Num of Std Step Trials=20
Max Error Tol=0.3
Flow Tol Ratio=0.001
Split Flow NTrial=30
Split Flow Tol=0.02
Split Flow Ratio=0.02
Log Output Level=0
Friction Slope Method=1
Unsteady Friction Slope Method=2
Unsteady Bridges Friction Slope Method=1
Global Log Level=0
CheckData=False
Run HTab=0
Run UNet=0
Run PostProcess=0
UNET Theta=0
UNET Theta Warmup=0
UNET ZTol=0
UNET ZSATol=0
UNET MxIter=0
UNET MaxInSteps=0
UNET DtIC=0
UNET DtMin=0
UNET MaxCRTS=0
UNET WFStab=0
UNET SFStab=0
UNET WFX=0
UNET SFX=0
UNET DSS MLevel=0
UNET DZMax Abort=0
UNET Convert EG Bridges=0
UNET Use Existing IB Tables=0
UNET Froude Limit=0
UNET Froude Power=0
Write IC File=0
Echo Input=False
Echo Output=False
Write Detailed=0

--- NP24.f01 (steady flow) ---

Flow Title=NFF Regression Equation
Program Version=4.00
Number of Profiles=1
Profile Names=P100yr
River Rch & RM=NP24,Main      ,3989.2
364.1515
River Rch & RM=NP24,Main      ,3689.2
364.1515
River Rch & RM=NP24,Main      ,3389.2
548.2336
River Rch & RM=NP24,Main      ,1490
585.0493
River Rch & RM=NP24,Main      ,1036.3
755.4939
River Rch & RM=NP24,Main      ,183.3
765.6739
Boundary for River Rch & Prof#=NP24,Main      ,1
Up Type=0
Dn Type=3
Dn Slope=0.183704

--- NP24.g01 (geometry) ---

Geom Title=USGS 3m DEM
Program Version=4.00

River Reach=NP24     ,Main
Reach XY= 30
     1968144.855      368087.539     1968063.258      368077.123
     1967960.827      368042.401     1967723.926      367923.345
     1967526.799      367856.637     1967410.701      367804.791
     1967311.522      367716.012     1967189.994      367525.040
     1967113.848      367434.589     1967080.774      367414.085
     1967017.937      367408.646     1966970.768      367389.778
     1966857.650      367293.251     1966803.930      367272.846
     1966609.139      367128.776     1966550.963      367062.739
     1966532.103      367002.385     1966498.776      366979.317
     1966525.084      366930.865     1966524.234      366907.082
     1966516.373      366870.919     1966484.510      366829.358
     1966103.333      366540.522     1966091.635      366349.155
     1966019.855      366222.956     1965986.869      366139.623
     1965896.591      365847.956     1965860.133      365781.984
     1965804.577      365585.803     1965704.474      365341.226

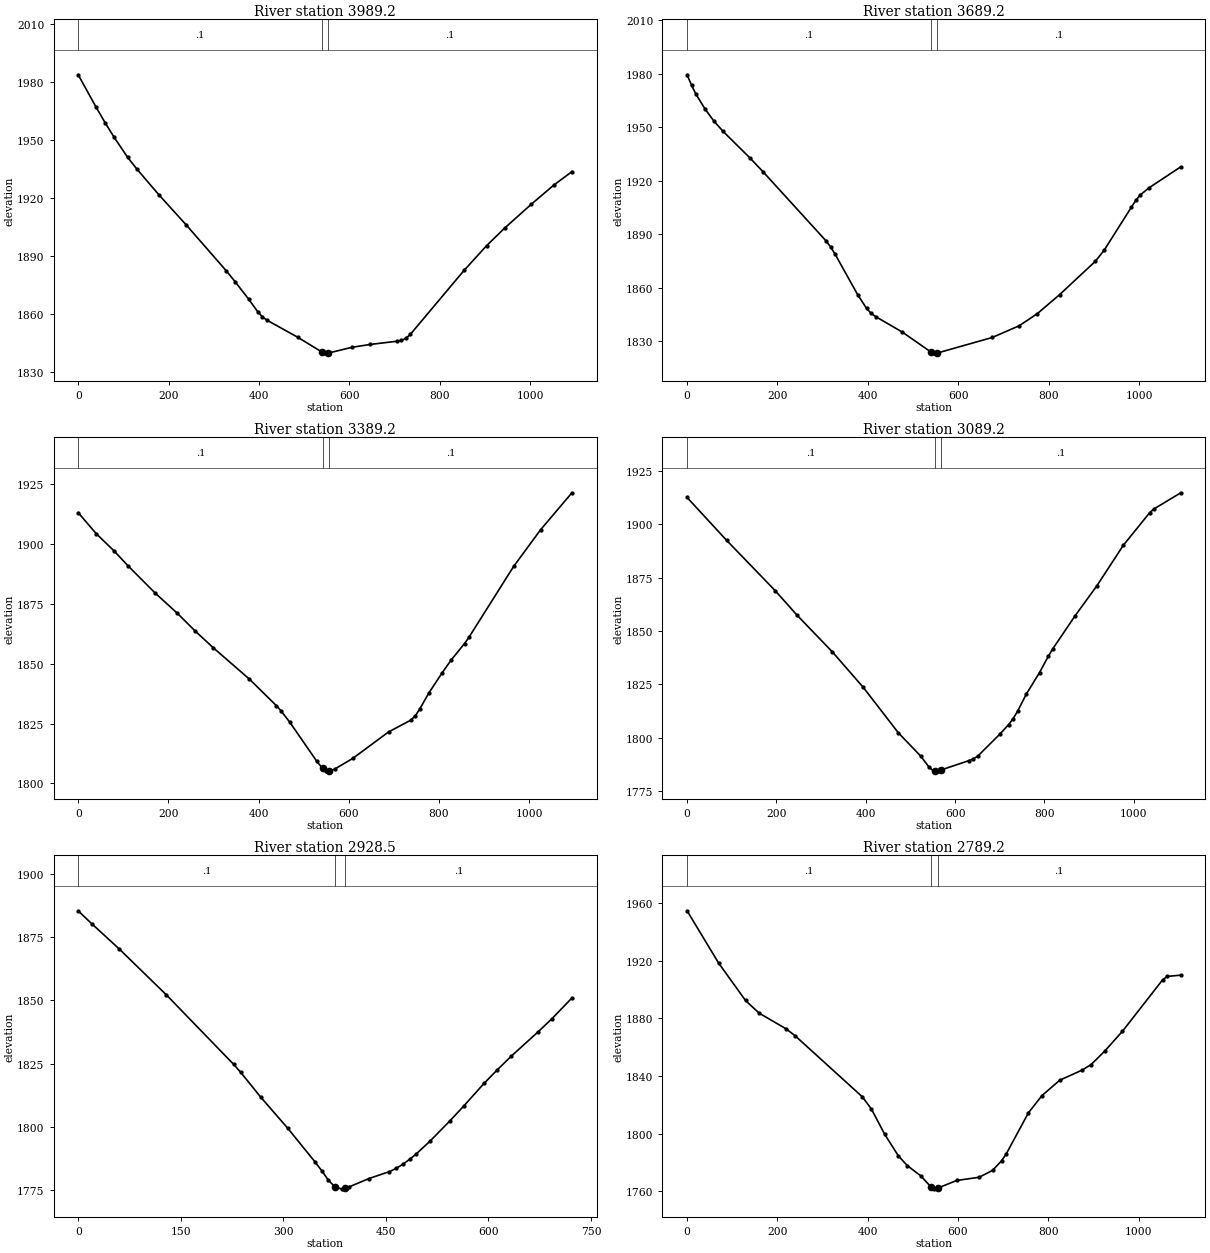
Type RM Length L Ch R = 1 ,3989.2,293.2,300,307.1
XS GIS Cut Line= 3
     1968212.118      367545.682     1968134.935      368086.273
     1968065.796      368627.865
#Sta/Elev= 30
       0 1983.61    39.7 1966.86    59.6 1958.85    79.4 1951.38   109.2 1941.08
   129.1 1935.17   178.7 1921.63   238.3 1906.31   327.6 1882.45   347.5 1876.73
   377.3 1867.74   397.1 1861.35   407.1 1858.78   417.0 1857.06   486.5 1848.06
   538.6 1840.62   546.1 1839.98   553.6 1840.03   605.6 1842.99   645.3 1844.44
   704.9 1846.11   714.8 1846.53   724.8 1847.54   734.7 1849.66   853.8 1882.73
   903.4 1895.42   943.2 1904.47  1002.7 1916.90  1052.4 1926.75  1092.1 1933.61
#Mann= 3 , 0 , 0
       0     0.1       0   538.6   0.045       0   553.6     0.1       0
Bank Sta=   538.6,   553.6
Exp/Cntr=0.3,0.1

Type RM Length L Ch R = 1 ,3689.2,301.3,300,297.7
XS GIS Cut Line= 3
     1968086.489      367497.767     1967852.754      367991.208
     1967619.018      368484.649
#Sta/Elev= 30
       0 1979.29     9.9 1973.45    19.8 1968.35    39.7 1960.15    59.6 1953.28
    79.4 1947.66   139.0 1932.72   168.8 1924.75   307.8 1886.10   317.7 1882.78
   327.6 1878.68   377.2 1856.13   397.1 1848.35   407.0 1845.64   417.0 1843.81
   476.5 1835.02   538.5 1824.09   546.0 1823.30   553.5 1823.35   675.0 1832.07
   734.6 1838.63   774.3 1845.33   824.0 1856.07   903.4 1874.83   923.2 1881.19
   982.8 1905.09   992.7 1908.93  1002.6 1912.00  1022.5 1916.06  1092.0 1927.72
#Mann= 3 , 0 , 0
       0     0.1       0   538.5   0.045       0   553.5     0.1       0
Bank Sta=   538.5,   553.5
Exp/Cntr=0.3,0.1

Type RM Length L Ch R = 1 ,3389.2,291.5,300,310.5
XS GIS Cut Line= 3
     1967784.858      367366.162     1967577.739      367874.768
     1967394.839      368388.630
#Sta/Elev= 30
       0 1913.00    39.9 1904.24    79.9 1896.97   109.8 1890.94   169.7 1879.63
   219.7 1871.02   259.6 1863.58   299.5 1856.63   379.4 1843.58   439.3 1832.50
   449.3 1830.39   469.3 1825.52   529.2 1809.21   541.7 1806.30   549.2 1805.17
   556.7 1805.16   569.0 1806.05   608.7 1810.46   688.0 1821.50   737.6 1826.44
   747.5 1828.23   757.4 1831.14   777.3 1837.70   807.0 1846.20   826.8 1851.49
   856.6 1858.40   866.5 1861.05   965.7 1890.64  1025.2 1905.87  1094.6 1921.28
#Mann= 3 , 0 , 0
       0     0.1       0   541.7   0.045       0   556.7     0.1       0
Bank Sta=   541.7,   556.7
Exp/Cntr=0.3,0.1

Type RM Length L Ch R = 1 ,3089.2,158.3,160.7,162
XS GIS Cut Line= 3
     1967709.909      367320.334     1967322.120      367727.092
     1966929.596      368102.548
#Sta/Elev= 30
       0 1912.60    88.7 1892.46   197.2 1868.93   246.5 1857.35   325.4 1840.17
   394.4 1823.58   473.2 1802.22   522.6 1791.45   542.3 1786.02   552.1 1784.30
   554.5 1784.31   562.0 1784.36   569.5 1784.91   631.1 1789.23   641.0 1790.05
   650.9 1791.36   700.2 1801.63   720.0 1806.16   729.9 1808.90   739.8 1812.32
   759.5 1820.43   789.1 1830.52   808.9 1838.21   818.8 1841.66   868.1 1856.94
   917.5 1871.21   976.8 1890.22  1036.0 1905.54  1045.9 1907.32  1105.2 1914.78
#Mann= 3 , 0 , 0
       0     0.1       0   554.5   0.045       0   569.5     0.1       0
Bank Sta=   554.5,   569.5
Exp/Cntr=0.3,0.1

Type RM Length L Ch R = 1 ,2928.5,139.3,139.3,139.7
XS GIS Cut Line= 2
     1967523.694      367347.064     1966972.996      367814.038
#Sta/Elev= 30
       0 1885.33    19.8 1880.23    59.4 1870.42   128.6 1852.23   227.5 1824.65
   237.4 1821.63   267.0 1811.73   306.6 1799.42   346.2 1786.23   356.1 1782.71
   366.0 1778.92   375.2 1776.40   385.7 1775.43   390.2 1775.80   395.6 1776.24
   425.3 1779.62   455.0 1782.32   464.9 1783.60   474.8 1785.24   484.6 1787.18
   494.5 1789.37   514.3 1794.32   544.0 1802.49   563.8 1808.22   593.4 1817.15
   613.2 1822.61   633.0 1827.85   672.6 1837.54   692.4 1842.61   722.0 1850.89
#Mann= 3 , 0 , 0
       0     0.1       0   375.2   0.045       0   390.2     0.1       0
Bank Sta=   375.2,   390.2
Exp/Cntr=0.3,0.1

Type RM Length L Ch R = 1 ,2789.2,91.2,84.3,77.2
XS GIS Cut Line= 3
     1967568.453      367130.523     1967149.821      367483.259
     1966727.046      367828.402
#Sta/Elev= 30
       0 1954.82    69.7 1918.59   129.4 1892.49   159.2 1883.77   219.0 1872.83
   238.9 1868.05   388.2 1825.49   408.1 1817.06   437.9 1799.32   467.8 1784.51
   487.7 1777.68   517.6 1770.54   539.9 1762.93   547.4 1761.34   554.9 1762.04
   597.0 1767.35   646.7 1769.58   676.4 1774.35   696.3 1780.99   706.2 1785.49
   755.8 1814.33   785.6 1826.28   825.3 1837.08   874.9 1844.10   894.7 1847.94
   924.5 1857.17   964.2 1871.10  1053.5 1907.01  1063.4 1909.23  1093.2 1910.10
#Mann= 3 , 0 , 0
       0     0.1       0   539.9   0.045       0   554.9     0.1       0
Bank Sta=   539.9,   554.9
Exp/Cntr=0.3,0.1

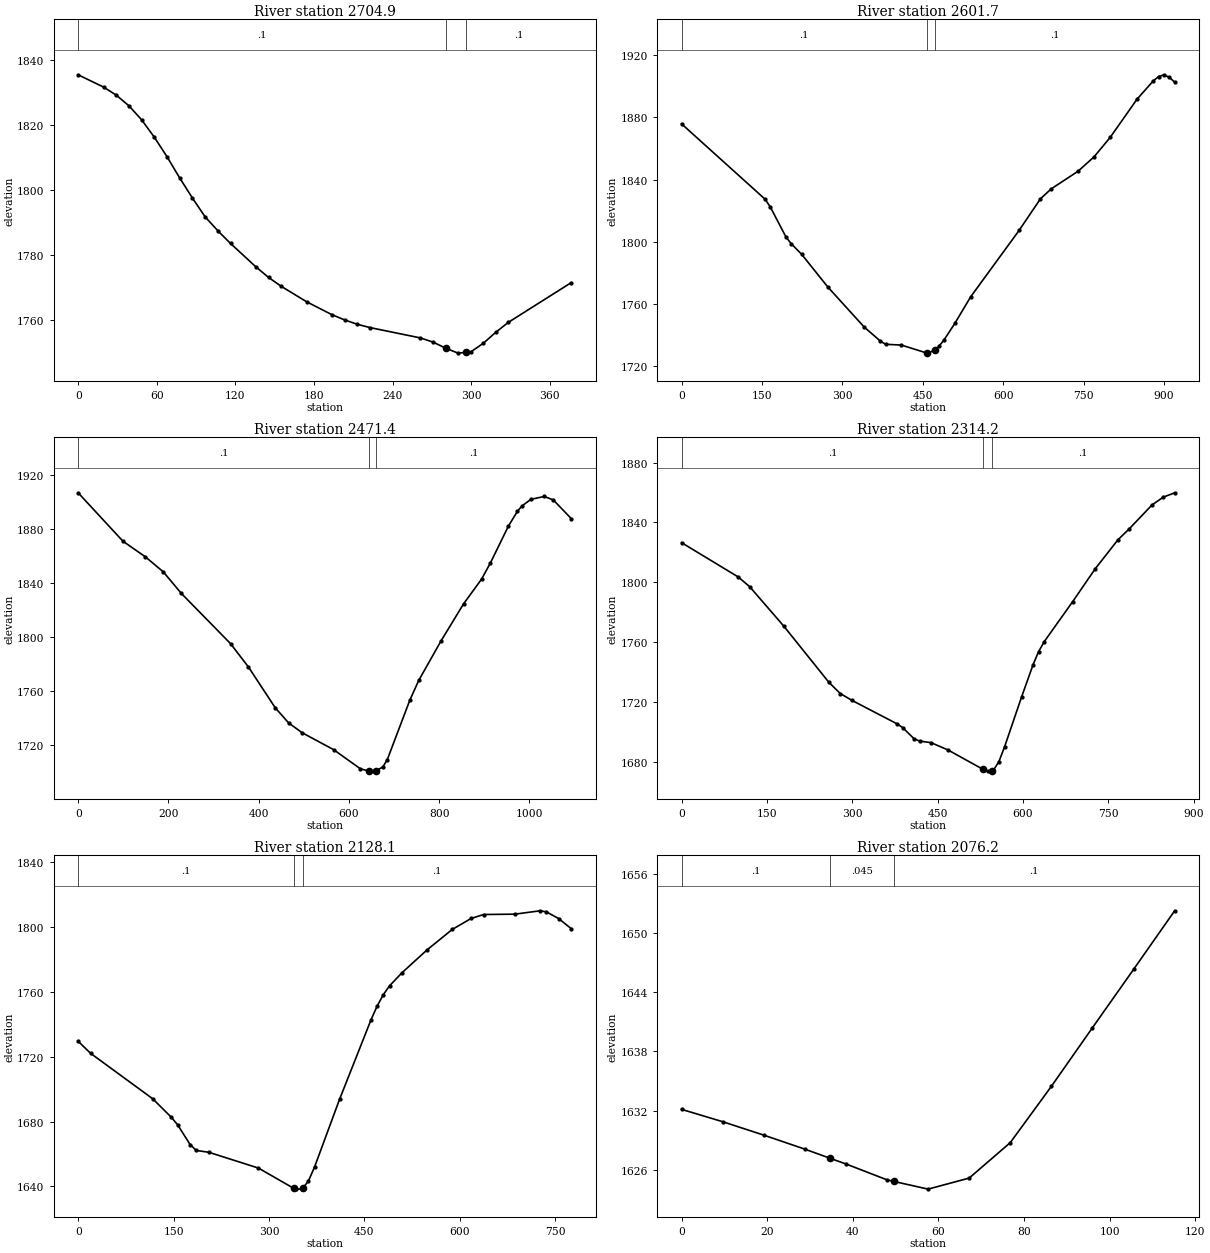
Type RM Length L Ch R = 1 ,2704.9,105.2,103.1,100.8
XS GIS Cut Line= 3
     1966887.768      367616.956     1967065.311      367466.824
     1967142.632      367345.523
#Sta/Elev= 30
       0 1835.46    19.4 1831.68    29.1 1829.20    38.8 1825.90    48.4 1821.62
    58.1 1816.26    67.8 1810.25    77.5 1803.70    87.2 1797.53    96.9 1791.73
   106.6 1787.45   116.3 1783.53   135.6 1776.35   145.3 1773.08   155.0 1770.34
   174.4 1765.57   193.8 1761.58   203.4 1759.99   213.1 1758.64   222.8 1757.62
   261.3 1754.44   270.9 1753.15   280.8 1751.24   290.0 1749.76   295.8 1749.97
   299.6 1750.10   309.2 1752.76   318.8 1756.18   328.4 1759.24   376.4 1771.47
#Mann= 3 , 0 , 0
       0     0.1       0   280.8   0.045       0   295.8     0.1       0
Bank Sta=   280.8,   295.8
Exp/Cntr=0.3,0.1

Type RM Length L Ch R = 1 ,2601.7,123.4,130.3,137.2
XS GIS Cut Line= 4
     1967345.788      367116.987     1967051.891      367289.500
     1966961.150      367466.248     1966672.843      367714.462
#Sta/Elev= 30
       0 1875.84   155.8 1827.36   165.5 1822.40   194.7 1803.08   204.5 1798.74
   224.0 1791.92   272.6 1770.95   340.8 1745.04   370.6 1736.14   380.5 1733.99
   410.3 1733.48   457.1 1728.40   460.0 1728.30   472.1 1730.23   479.9 1732.60
   489.8 1736.84   509.7 1747.37   539.5 1764.61   629.6 1807.23   669.6 1827.63
   689.6 1834.01   739.7 1845.36   769.7 1854.67   799.8 1867.20   849.8 1891.75
   879.9 1903.45   889.9 1906.29   899.9 1907.42   909.9 1905.84   919.9 1902.75
#Mann= 3 , 0 , 0
       0     0.1       0   457.1   0.045       0   472.1     0.1       0
Bank Sta=   457.1,   472.1
Exp/Cntr=0.3,0.1

Type RM Length L Ch R = 1 ,2471.4,157.8,157,156.2
XS GIS Cut Line= 3
     1967332.461      366841.510     1966966.560      367246.615
     1966582.821      367635.909
#Sta/Elev= 30
       0 1906.62    99.2 1870.86   148.9 1859.33   188.6 1848.24   228.3 1832.40
   337.5 1795.23   377.2 1777.98   436.7 1747.80   466.5 1736.58   496.3 1729.37
   565.8 1716.93   625.4 1702.72   644.8 1701.05   655.2 1701.02   659.8 1701.25
   675.1 1704.10   685.0 1709.60   734.7 1753.30   754.6 1768.04   804.3 1797.38
   854.0 1824.63   893.7 1842.79   913.6 1854.93   953.4 1882.11   973.2 1892.90
   983.2 1896.89  1003.1 1901.82  1032.9 1903.92  1052.8 1901.37  1092.5 1887.61
#Mann= 3 , 0 , 0
       0     0.1       0   644.8   0.045       0   659.8     0.1       0
Bank Sta=   644.8,   659.8
Exp/Cntr=0.3,0.1

Type RM Length L Ch R = 1 ,2314.2,181,186.1,185.9
XS GIS Cut Line= 2
     1967126.950      366841.569     1966539.957      367478.876
#Sta/Elev= 30
       0 1826.50    99.6 1803.52   119.5 1797.08   179.3 1770.77   258.9 1732.99
   278.8 1725.53   298.8 1721.04   378.4 1705.27   388.4 1702.74   408.3 1695.32
   418.3 1693.67   438.2 1692.65   468.1 1687.75   530.1 1674.68   537.8 1673.57
   545.1 1673.94   547.8 1674.08   557.7 1679.99   567.7 1689.97   597.6 1723.36
   617.5 1744.63   627.4 1753.60   637.4 1760.31   687.2 1787.00   727.0 1809.08
   766.8 1828.43   786.8 1835.80   826.6 1851.72   846.5 1856.98   866.4 1859.86
#Mann= 3 , 0 , 0
       0     0.1       0   530.1   0.045       0   545.1     0.1       0
Bank Sta=   530.1,   545.1
Exp/Cntr=0.3,0.1

Type RM Length L Ch R = 1 ,2128.1,46.1,51.9,62.9
XS GIS Cut Line= 3
     1966932.541      367006.530     1966620.046      367119.735
     1966322.224      367447.541
#Sta/Elev= 30
       0 1729.40    19.6 1721.98   117.3 1693.99   146.6 1682.58   156.4 1677.96
   176.0 1665.84   185.7 1662.20   205.3 1661.08   283.5 1651.34   338.6 1638.94
   342.2 1638.38   352.0 1638.43   353.6 1639.21   361.9 1643.26   371.7 1652.02
   411.1 1693.79   460.3 1742.48   470.2 1751.23   480.0 1758.23   489.8 1763.67
   509.5 1771.75   548.9 1785.81   588.3 1798.32   617.8 1805.04   637.5 1807.49
   686.7 1807.71   726.0 1809.76   735.9 1809.20   755.6 1804.97   775.3 1798.79
#Mann= 3 , 0 , 0
       0     0.1       0   338.6   0.045       0   353.6     0.1       0
Bank Sta=   338.6,   353.6
Exp/Cntr=0.3,0.1

Type RM Length L Ch R = 1 ,2076.2,51.8,53.5,55.2
XS GIS Cut Line= 2
     1966615.485      367076.410     1966507.779      367117.244
#Sta/Elev= 15
       0 1632.13     9.6 1630.88    19.2 1629.52    28.8 1628.10    34.6 1627.19
    38.4 1626.60    48.0 1624.99    49.6 1624.83    57.6 1624.05    67.2 1625.17
    76.8 1628.76    86.4 1634.46    96.0 1640.40   105.6 1646.30   115.2 1652.24
#Mann= 3 , 0 , 0
       0     0.1       0    34.6   0.045       0    49.6     0.1       0
Bank Sta=    34.6,    49.6
Exp/Cntr=0.3,0.1

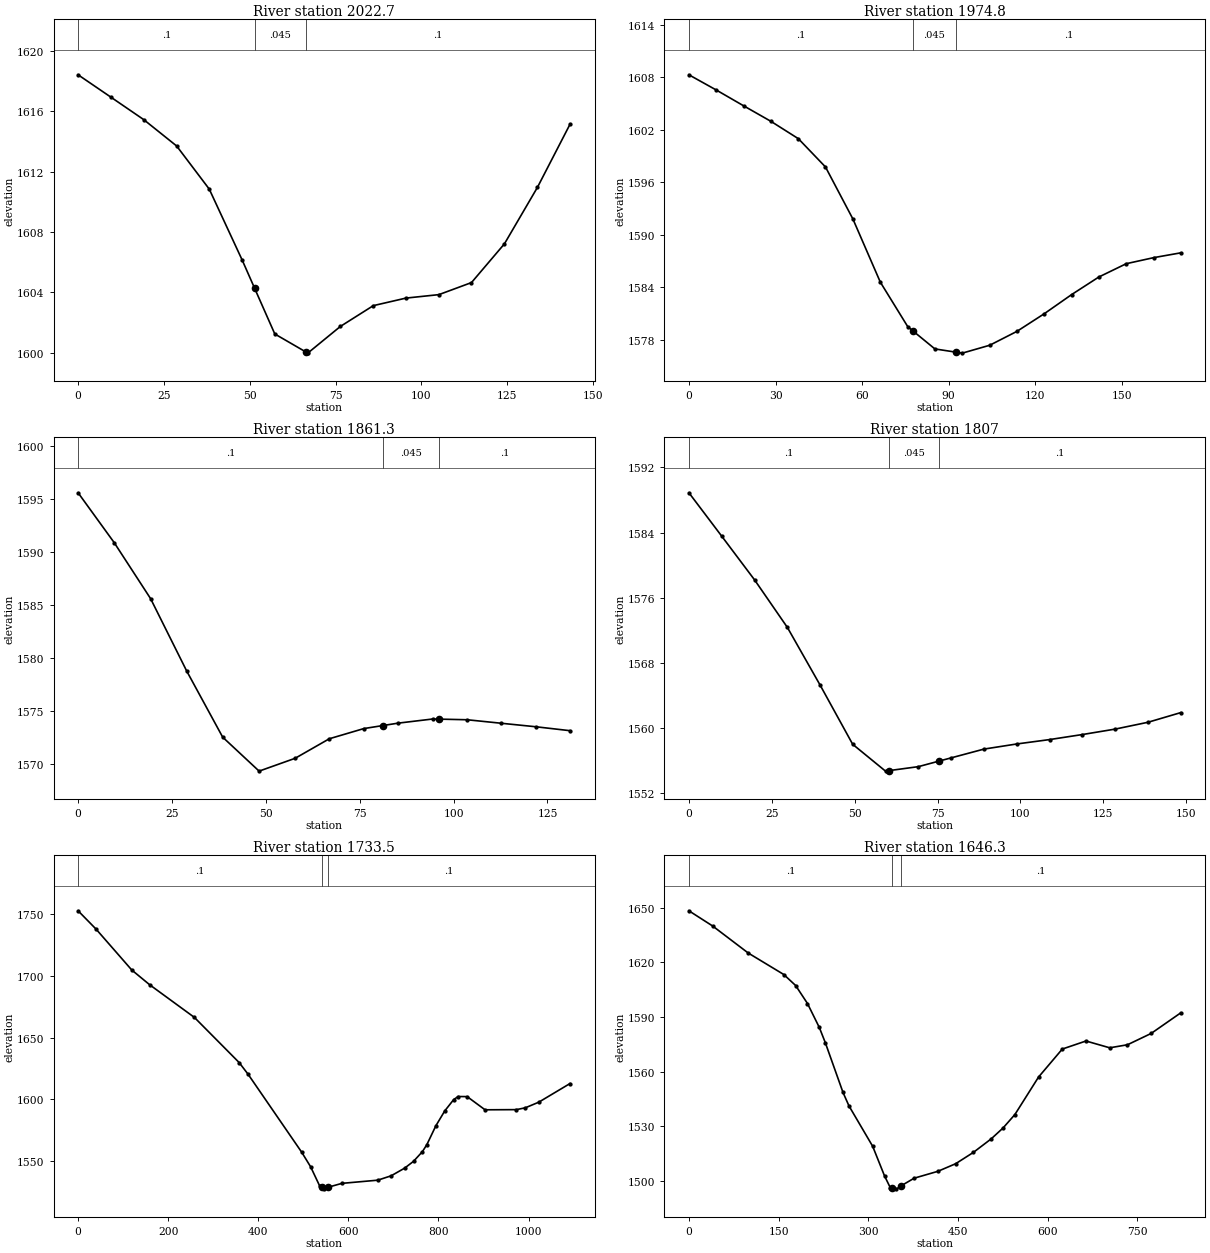
Type RM Length L Ch R = 1 ,2022.7,49.2,47.9,49
XS GIS Cut Line= 2
     1966603.057      367032.026     1966465.170      367071.084
#Sta/Elev= 18
       0 1618.43     9.6 1616.94    19.1 1615.46    28.7 1613.71    38.2 1610.85
    47.8 1606.14    51.4 1604.28    57.3 1601.24    66.4 1600.04    66.9 1599.97
    76.4 1601.74    86.0 1603.12    95.5 1603.62   105.1 1603.85   114.6 1604.65
   124.2 1607.22   133.8 1610.96   143.3 1615.15
#Mann= 3 , 0 , 0
       0     0.1       0    51.4   0.045       0    66.4     0.1       0
Bank Sta=    51.4,    66.4
Exp/Cntr=0.3,0.1

Type RM Length L Ch R = 1 ,1974.8,131.4,113.1,1972.2
XS GIS Cut Line= 2
     1966612.328      366974.425     1966451.362      367030.448
#Sta/Elev= 21
       0 1608.27     9.5 1606.53    18.9 1604.74    28.4 1602.96    37.9 1600.98
    47.3 1597.75    56.8 1591.81    66.3 1584.60    75.8 1579.52    77.5 1579.06
    85.2 1576.98    92.5 1576.61    94.7 1576.50   104.2 1577.40   113.6 1578.98
   123.1 1581.00   132.6 1583.19   142.0 1585.19   151.5 1586.71   161.0 1587.40
   170.4 1587.95
#Mann= 3 , 0 , 0
       0     0.1       0    77.5   0.045       0    92.5     0.1       0
Bank Sta=    77.5,    92.5
Exp/Cntr=0.3,0.1

Type RM Length L Ch R = 1 ,1861.3,44.4,54.3,2202.1
XS GIS Cut Line= 3
     1966581.260      366850.396     1966542.399      366893.153
     1966500.234      366953.072
#Sta/Elev= 17
       0 1595.58     9.6 1590.89    19.3 1585.61    28.9 1578.80    38.5 1572.56
    48.2 1569.36    57.8 1570.57    66.9 1572.41    76.1 1573.37    81.1 1573.65
    85.2 1573.88    94.4 1574.27    96.1 1574.26   103.6 1574.20   112.7 1573.87
   121.9 1573.54   131.0 1573.17
#Mann= 3 , 0 , 0
       0     0.1       0    81.1   0.045       0    96.1     0.1       0
Bank Sta=    81.1,    96.1
Exp/Cntr=0.3,0.1

Type RM Length L Ch R = 1 ,1807,75.5,73.4,75.9
XS GIS Cut Line= 3
     1966562.026      366819.377     1966504.623      366873.821
     1966467.932      366932.606
#Sta/Elev= 18
       0 1588.88     9.9 1583.54    19.8 1578.17    29.7 1572.32    39.6 1565.21
    49.4 1557.95    59.3 1554.65    60.5 1554.72    69.2 1555.20    75.5 1555.89
    79.1 1556.28    89.0 1557.36    98.9 1557.99   108.8 1558.53   118.7 1559.15
   128.6 1559.82   138.5 1560.66   148.4 1561.85
#Mann= 3 , 0 , 0
       0     0.1       0    60.5   0.045       0    75.5     0.1       0
Bank Sta=    60.5,    75.5
Exp/Cntr=0.3,0.1

Type RM Length L Ch R = 1 ,1733.5,87.8,87.2,86.5
XS GIS Cut Line= 3
     1966827.565      366408.999     1966462.312      366814.839
     1966097.058      367220.678
#Sta/Elev= 30
       0 1752.92    39.7 1738.13   119.1 1704.93   158.8 1692.98   258.1 1666.51
   357.4 1629.93   377.2 1620.49   496.4 1557.18   516.2 1545.38   536.1 1529.98
   540.4 1528.81   546.0 1527.29   555.4 1528.87   585.7 1531.97   665.1 1534.54
   694.9 1538.09   724.7 1544.27   744.6 1549.83   764.4 1557.71   774.3 1563.42
   794.2 1578.63   814.0 1590.74   833.9 1599.94   843.8 1602.38   863.7 1602.29
   903.4 1591.60   972.9 1591.74   992.7 1593.21  1022.5 1597.75  1092.0 1612.89
#Mann= 3 , 0 , 0
       0     0.1       0   540.4   0.045       0   555.4     0.1       0
Bank Sta=   540.4,   555.4
Exp/Cntr=0.3,0.1

Type RM Length L Ch R = 1 ,1646.3,92.1,91.3,90.4
XS GIS Cut Line= 2
     1966617.524      366497.759     1966085.038      367124.583
#Sta/Elev= 30
       0 1648.20    39.6 1639.88    99.1 1625.06   158.6 1613.27   178.4 1607.24
   198.2 1597.37   218.0 1584.22   227.9 1575.99   257.6 1548.60   267.6 1541.20
   307.2 1519.08   327.0 1502.86   336.9 1496.21   340.3 1495.99   346.8 1495.58
   355.3 1497.50   376.6 1501.58   416.2 1505.34   445.9 1509.50   475.6 1515.72
   505.4 1523.14   525.2 1529.10   545.0 1536.47   584.6 1557.05   624.3 1572.40
   663.9 1576.81   703.6 1573.08   733.3 1574.75   772.9 1580.96   822.5 1592.28
#Mann= 3 , 0 , 0
       0     0.1       0   340.3   0.045       0   355.3     0.1       0
Bank Sta=   340.3,   355.3
Exp/Cntr=0.3,0.1

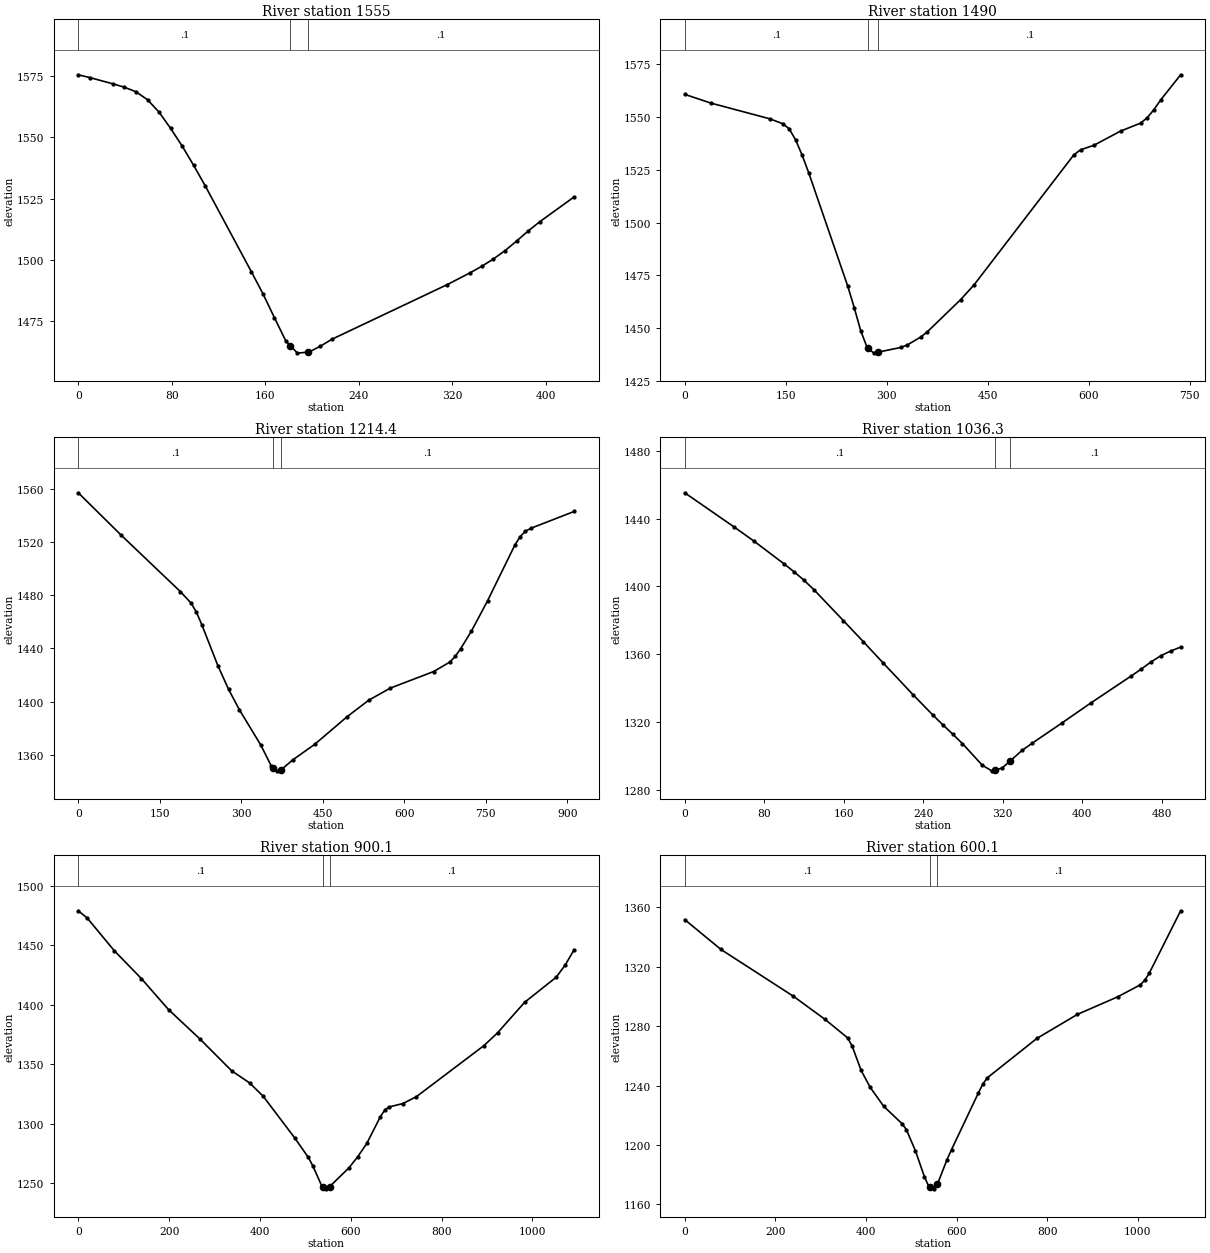
Type RM Length L Ch R = 1 ,1555,63,64.8,66.6
XS GIS Cut Line= 2
     1966442.474      366552.134     1966179.900      366885.462
#Sta/Elev= 30
       0 1575.45     9.9 1574.32    29.6 1571.78    39.5 1570.39    49.3 1568.55
    59.2 1565.30    69.1 1560.23    78.9 1553.68    88.8 1546.46    98.7 1538.55
   108.6 1530.20   148.0 1495.26   157.9 1486.32   167.8 1476.47   177.6 1466.95
   181.4 1465.06   187.5 1462.03   196.4 1462.42   197.4 1462.46   207.2 1464.88
   217.1 1467.71   315.8 1489.98   335.5 1494.83   345.4 1497.47   355.2 1500.40
   365.1 1503.78   375.0 1507.70   384.8 1511.74   394.7 1515.52   424.3 1525.70
#Mann= 3 , 0 , 0
       0     0.1       0   181.4   0.045       0   196.4     0.1       0
Bank Sta=   181.4,   196.4
Exp/Cntr=0.3,0.1

Type RM Length L Ch R = 1 ,1490,258.4,275.3,291.4
XS GIS Cut Line= 3
     1966460.818      366457.927     1966277.618      366657.764
     1965960.826      366998.799
#Sta/Elev= 30
       0 1560.75    38.7 1556.63   125.9 1549.21   145.2 1546.90   154.9 1544.51
   164.6 1539.22   174.3 1531.97   184.0 1523.70   242.1 1469.89   251.7 1459.73
   261.4 1448.72   271.1 1440.68   272.2 1440.40   281.0 1438.18   287.2 1438.64
   320.6 1440.85   330.5 1442.04   350.3 1445.76   360.2 1448.24   409.8 1463.53
   429.6 1470.47   578.1 1532.16   588.0 1534.51   607.8 1536.64   647.4 1543.36
   677.2 1547.13   687.1 1549.74   697.0 1553.55   706.9 1558.09   736.6 1570.01
#Mann= 3 , 0 , 0
       0     0.1       0   272.2   0.045       0   287.2     0.1       0
Bank Sta=   272.2,   287.2
Exp/Cntr=0.3,0.1

Type RM Length L Ch R = 1 ,1214.4,184.3,178,172.2
XS GIS Cut Line= 3
     1966463.963      366435.915     1966100.679      366475.575
     1965558.212      366548.781
#Sta/Elev= 30
       0 1556.83    79.0 1524.98   187.7 1482.70   207.4 1474.07   217.3 1467.27
   227.2 1457.88   256.8 1427.10   276.6 1409.20   296.3 1393.99   335.8 1367.43
   355.6 1351.32   358.6 1350.23   365.4 1347.76   373.6 1348.91   395.3 1356.34
   435.1 1367.88   494.8 1388.64   534.6 1401.03   574.4 1410.13   654.1 1422.57
   683.9 1429.68   693.9 1434.00   703.8 1439.69   723.7 1452.95   753.6 1475.92
   803.4 1517.40   813.3 1523.93   823.2 1527.98   833.2 1530.21   912.8 1542.83
#Mann= 3 , 0 , 0
       0     0.1       0   358.6   0.045       0   373.6     0.1       0
Bank Sta=   358.6,   373.6
Exp/Cntr=0.3,0.1

Type RM Length L Ch R = 1 ,1036.3,136.3,136.3,136.6
XS GIS Cut Line= 2
     1966362.156      366183.167     1965901.078      366374.202
#Sta/Elev= 30
       0 1455.23    49.9 1434.97    69.9 1426.61    99.8 1413.34   109.8 1408.71
   119.8 1403.75   129.8 1398.15   159.7 1379.76   179.7 1367.37   199.6 1354.84
   229.6 1336.16   249.5 1324.17   259.5 1318.43   269.5 1312.90   279.5 1307.19
   299.4 1294.46   309.4 1290.95   312.3 1291.49   319.4 1292.80   327.3 1296.82
   339.4 1303.14   349.4 1307.31   379.3 1319.24   409.2 1331.38   449.2 1347.04
   459.2 1351.10   469.1 1355.30   479.1 1359.05   489.1 1361.84   499.1 1364.16
#Mann= 3 , 0 , 0
       0     0.1       0   312.3   0.045       0   327.3     0.1       0
Bank Sta=   312.3,   327.3
Exp/Cntr=0.3,0.1

Type RM Length L Ch R = 1 ,900.1,298.6,299.9,300.2
XS GIS Cut Line= 3
     1966509.716      365976.578     1966004.893      366184.720
     1965496.725      366384.402
#Sta/Elev= 30
       0 1479.11    19.9 1472.92    79.4 1445.50   139.0 1422.12   198.6 1396.12
   268.1 1371.29   337.6 1344.69   377.3 1334.42   407.0 1323.32   476.6 1288.20
   506.3 1272.01   516.3 1264.91   536.1 1247.86   538.5 1247.22   546.0 1245.20
   553.5 1247.34   595.7 1262.95   615.5 1272.50   635.4 1283.67   665.2 1306.05
   675.1 1311.78   685.0 1314.30   714.8 1317.12   744.6 1322.92   893.5 1365.88
   923.3 1376.57   982.8 1402.17  1052.3 1423.26  1072.2 1433.49  1092.0 1446.46
#Mann= 3 , 0 , 0
       0     0.1       0   538.5   0.045       0   553.5     0.1       0
Bank Sta=   538.5,   553.5
Exp/Cntr=0.3,0.1

Type RM Length L Ch R = 1 ,600.1,300,300,300.6
XS GIS Cut Line= 3
     1966428.335      365722.722     1965909.137      365901.154
     1965398.660      366093.284
#Sta/Elev= 30
       0 1351.66    79.9 1331.60   239.6 1300.13   309.4 1284.59   359.4 1272.10
   369.3 1266.63   389.3 1250.15   409.3 1238.75   439.2 1226.01   479.1 1214.46
   489.1 1210.38   509.1 1196.04   529.0 1178.56   539.0 1171.84   541.5 1171.46
   549.0 1170.30   556.5 1173.60   558.9 1174.65   578.8 1190.17   588.7 1196.88
   648.2 1235.16   658.1 1241.15   668.0 1245.30   777.1 1271.74   866.4 1287.88
   955.6 1299.75  1005.2 1307.77  1015.1 1310.84  1025.0 1315.54  1094.4 1357.62
#Mann= 3 , 0 , 0
       0     0.1       0   541.5   0.045       0   556.5     0.1       0
Bank Sta=   541.5,   556.5
Exp/Cntr=0.3,0.1

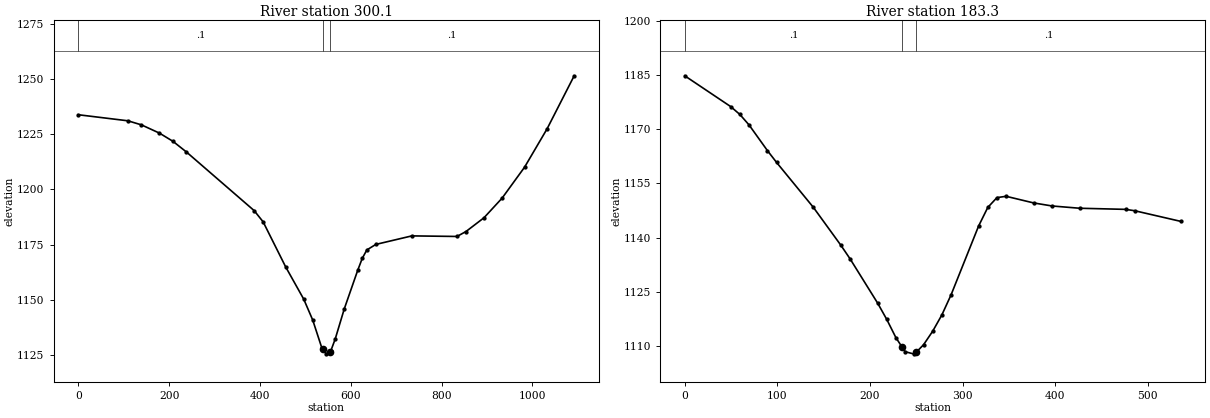
Type RM Length L Ch R = 1 ,300.1,117,116.8,116.5
XS GIS Cut Line= 3
     1966332.437      365441.966     1965815.831      365618.699
     1965299.226      365795.433
#Sta/Elev= 30
       0 1233.75   109.2 1231.01   139.0 1229.17   178.7 1225.43   208.5 1221.71
   238.2 1216.88   387.2 1190.38   407.0 1185.29   456.6 1164.92   496.4 1150.32
   516.2 1140.87   536.1 1128.34   538.5 1127.64   546.0 1125.44   553.5 1126.49
   555.9 1126.83   565.8 1132.31   585.7 1145.91   615.5 1163.48   625.4 1168.81
   635.4 1172.58   655.2 1175.08   734.6 1178.94   833.9 1178.68   853.8 1180.92
   893.4 1187.14   933.2 1196.00   982.8 1210.03  1032.4 1227.39  1092.0 1251.36
#Mann= 3 , 0 , 0
       0     0.1       0   538.5   0.045       0   553.5     0.1       0
Bank Sta=   538.5,   553.5
Exp/Cntr=0.3,0.1

Type RM Length L Ch R = 1 ,183.3,182.2,183.3,184.4
XS GIS Cut Line= 2
     1966000.658      365429.510     1965495.948      365608.753
#Sta/Elev= 30
       0 1184.83    49.6 1176.30    59.5 1174.12    69.4 1171.22    89.3 1164.09
    99.2 1160.81   138.9 1148.37   168.6 1137.87   178.5 1134.12   208.3 1121.84
   218.2 1117.30   228.1 1112.24     235 1109.54   238.0 1108.37   248.0 1107.70
     250 1108.23   257.9 1110.30   267.8 1114.06   277.7 1118.57   287.6 1124.11
   317.4 1143.22   327.3 1148.36   337.2 1151.08   347.1 1151.44   376.9 1149.60
   396.7 1148.76   426.5 1148.13   476.1 1147.82   486.0 1147.44   535.6 1144.50
#Mann= 3 , 0 , 0
       0     0.1       0     235   0.045       0     250     0.1       0
Bank Sta=     235,     250
Exp/Cntr=0.3,0.1